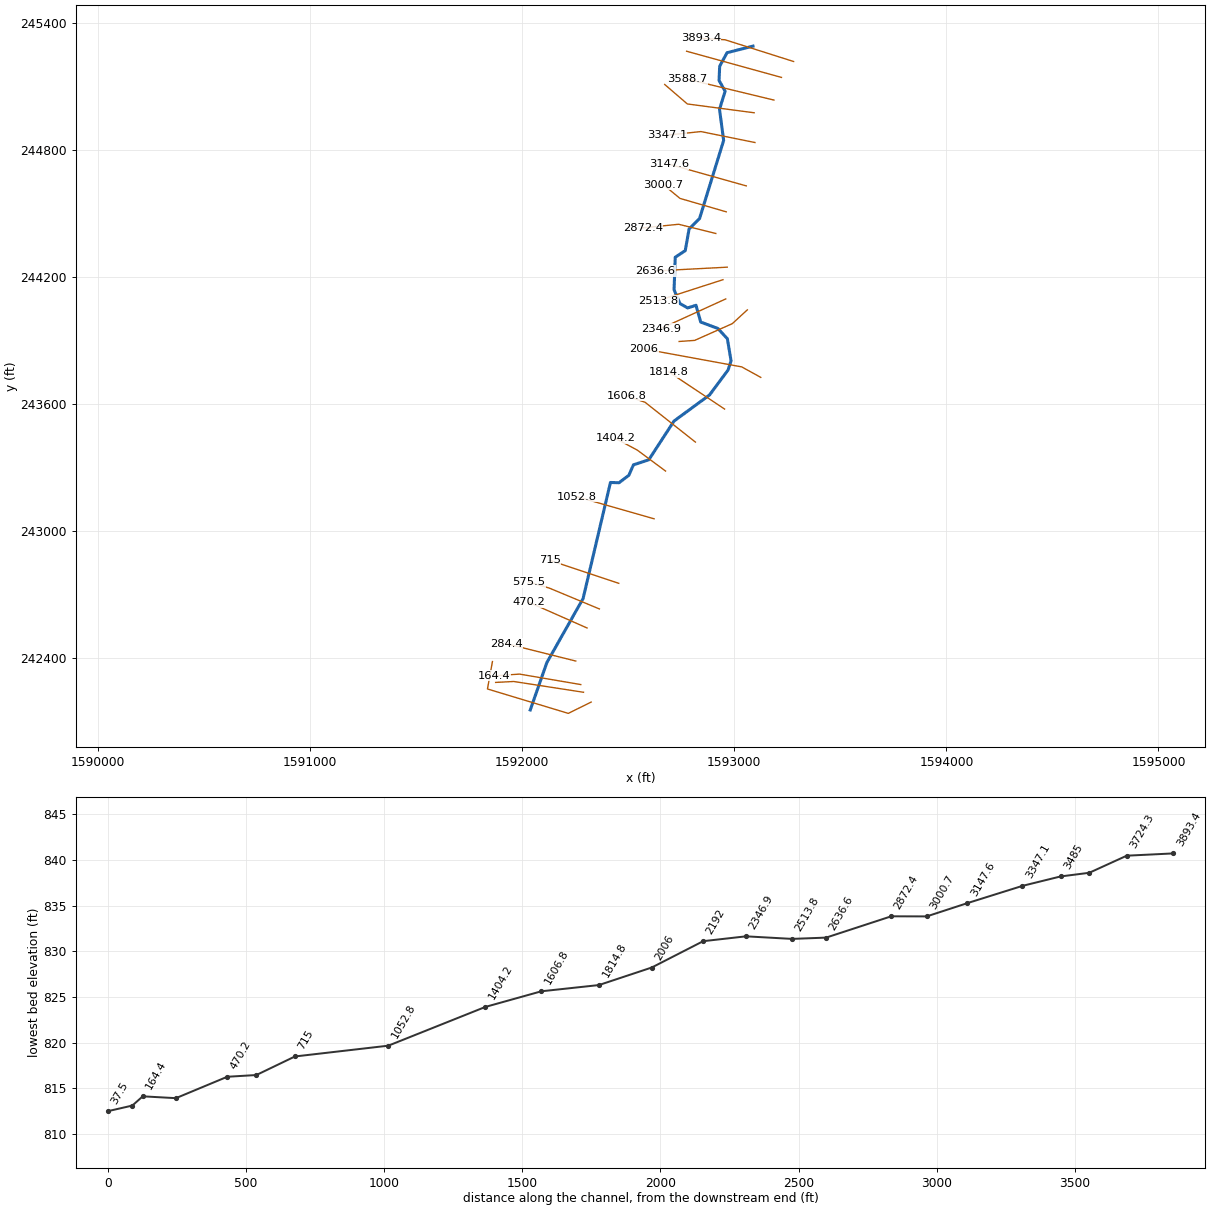
--- UPPERRN.prj (project) ---

Proj Title=UPPERRN
Current Plan=p01
Default Exp/Contr=0,0
English Units
Geom File=g01
Flow File=f01
Plan File=p01
BEGIN DESCRIPTION:
END DESCRIPTION:
DSS Export Rating Curves= 0
DSS Export Rating Curve Sorted= 0
DSS Export Volume Flow Curves= 0
DXF OffsetX= 0
DXF OffsetY= 0
DXF ScaleX= 0
DXF ScaleY= 0

--- UPPERRN.p01 (plan) ---

Plan Title=Floodplain
Program Version=4.00
Geom File=g01
Flow File=f01
K Sum by GR=0
Std Step Tol=0.01
Critical Tol=0.01
Num of Std Step Trials=20
Max Error Tol=0.3
Flow Tol Ratio=0.001
Split Flow NTrial=30
Split Flow Tol=0.02
Split Flow Ratio=0.02
Log Output Level=0
Friction Slope Method=1
Unsteady Friction Slope Method=2
Unsteady Bridges Friction Slope Method=1
Global Log Level=0
CheckData=False
Run HTab=0
Run UNet=0
Run PostProcess=0
UNET Theta=0
UNET Theta Warmup=0
UNET ZTol=0
UNET ZSATol=0
UNET MxIter=0
UNET MaxInSteps=0
UNET DtIC=0
UNET DtMin=0
UNET MaxCRTS=0
UNET WFStab=0
UNET SFStab=0
UNET WFX=0
UNET SFX=0
UNET DSS MLevel=0
UNET DZMax Abort=0
UNET Convert EG Bridges=0
UNET Use Existing IB Tables=0
UNET Froude Limit=0
UNET Froude Power=0
Write IC File=0
Echo Input=False
Echo Output=False
Write Detailed=0

--- UPPERRN.f01 (steady flow) ---

Flow Title=NFF Regression Equation
Program Version=4.10
Number of Profiles= 1
Profile Names=P100yr
River Rch & RM=UPPERRN,Main            ,3893.4
1056.729
River Rch & RM=UPPERRN,Main            ,575.5
 1111.93
River Rch & RM=UPPERRN,Main            ,284.4
1112.583
Boundary for River Rch & Prof#=UPPERRN,Main            , 1
Up Type= 0
Dn Type= 3
Dn Slope=0.00651
DSS Import GetInterval= 0
DSS Import GetPeak= 0
DSS Import FillOption= 0

--- UPPERRN.g01 (geometry) ---

Geom Title=USGS 10m DEM
Program Version=4.10

River Reach=UPPERRN         ,Main
Reach XY= 30
     1593087.951      245291.486     1592965.515      245260.267
     1592930.792      245196.378     1592928.014      245129.017
     1592956.487      245078.322     1592930.098      244992.906
     1592949.542      244845.684     1592835.868      244476.378
     1592786.562      244427.072     1592768.507      244324.989
     1592721.284      244293.739     1592715.729      244140.267
     1592743.507      244074.989     1592779.617      244054.156
     1592819.201      244066.656     1592841.423      243987.489
     1592922.673      243956.934     1592967.118      243908.323
     1592984.479      243804.156      1592970.59        243761.1
      1592882.76      243642.524     1592715.572      243519.607
     1592596.562      243336.534     1592524.166      243312.576
     1592502.541      243263.151       1592456.1      243227.995
     1592415.735      243229.297     1592286.829       242681.12
     1592115.605      242377.599     1592037.548      242154.262

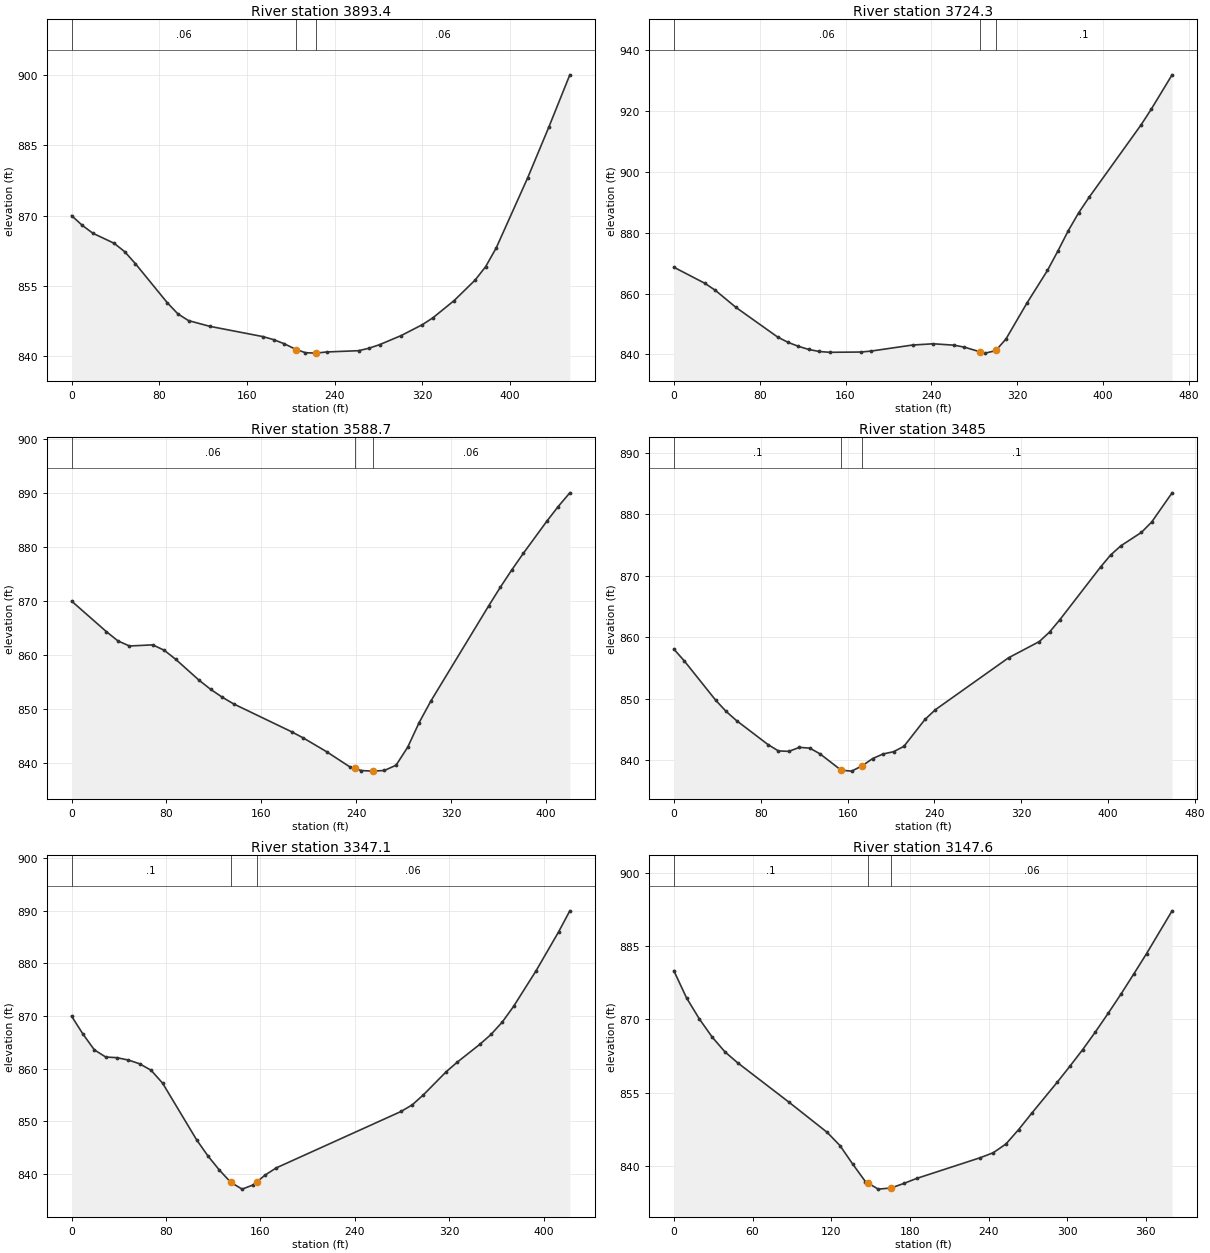
Type RM Length L Ch R = 1 ,3893.4  ,170.7,169,139.5
XS GIS Cut Line= 3
     1593279.585      245218.714     1592956.074      245321.537
     1592841.094       245328.25
#Sta/Elev= 30
       0     870     9.7  867.94    19.4  866.25    38.8  864.11    48.5  862.31
    58.2  859.77    87.3  851.45      97  849.06   106.7  847.63   126.1  846.41
   174.6  844.22   184.3  843.58     194   842.7   204.9  841.47   213.4  840.79
   223.1   840.7   232.8  840.95   261.9  841.22   271.6  841.76   281.3  842.53
   300.7  844.44   320.1  846.77   329.8  848.25   349.1  851.91   368.2  856.27
   377.8  859.13   387.4   863.1   416.2  878.09   435.4  888.84   454.6     900
#Mann= 3 , 0 , 0
       0     .06       0   204.9    .045       0   223.1     .06       0
Bank Sta=204.9,223.1
XS Rating Curve= 0 ,0
Exp/Cntr=0.3,0.1

Type RM Length L Ch R = 1 ,3724.3  ,138.9,135.6,129.1
XS GIS Cut Line= 2
     1593222.306      245143.582     1592774.911      245267.274
#Sta/Elev= 30
       0  868.67      29  863.37    38.7  861.07      58  855.44    96.7  845.74
   106.4  843.99     116  842.69   125.7  841.66   135.4  840.99   145.1  840.72
   174.1  840.81   183.7  841.12   222.4  843.11   241.8  843.52   261.1  843.06
   270.8   842.4   285.3  840.88   290.1  840.45   299.8  841.25   300.3  841.45
   309.4  845.07   328.8  856.79   348.1  867.62   357.8  873.99   367.5  880.67
   377.2  886.56   386.8  891.59   435.2  915.37   444.8  920.58   464.2  931.86
#Mann= 3 , 0 , 0
       0     .06       0   285.3    .045       0   300.3      .1       0
Bank Sta=285.3,300.3
XS Rating Curve= 0 ,0
Exp/Cntr=0.3,0.1

Type RM Length L Ch R = 1 ,3588.7  ,97.5,103.7,112.6
XS GIS Cut Line= 2
     1593186.848      245036.437      1592778.65      245135.315
#Sta/Elev= 30
       0     870    29.3  864.36    39.1  862.64    48.8   861.7    68.4  861.91
    78.1  860.91    87.9  859.22   107.4  855.39   117.2   853.7     127  852.24
   136.8  850.98   185.6  845.84   195.4   844.7   214.9  842.18   234.4  839.39
   238.8  839.08   244.2  838.69   253.8  838.58   263.7   838.7   273.5  839.67
   283.3  842.99     293  847.56   302.8  851.51   351.6  869.12   361.4  872.55
   371.2   875.8   380.9  878.85   400.5  884.72   410.2  887.47     420     890
#Mann= 3 , 0 , 0
       0     .06       0   238.8    .045       0   253.8     .06       0
Bank Sta=238.8,253.8
XS Rating Curve= 0 ,0
Exp/Cntr=0.3,0.1

Type RM Length L Ch R = 1 ,3485    ,139.3,137.9,136.3
XS GIS Cut Line= 3
     1593093.487      244976.476     1592778.383      245018.142
     1592671.612      245110.156
#Sta/Elev= 30
       0  858.06     9.6  856.14    38.5  849.74    48.2   847.9    57.8   846.4
    86.7  842.51    96.3  841.47     106   841.4   115.6  842.05   125.2  841.93
   134.8  840.97   154.1  838.33   163.7  838.18   173.4  839.04     183  840.22
   192.6  840.97   202.3  841.34   211.9  842.22   231.2  846.59   240.8  848.18
   308.2  856.64   336.6  859.29     346  860.84   355.4  862.83     393  871.44
   402.4  873.42   411.8   874.9   430.6  877.07     440  878.75   458.8  883.51
#Mann= 3 , 0 , 0
       0      .1       0   154.1    .045       0   173.4      .1       0
Bank Sta=154.1,173.4
XS Rating Curve= 0 ,0
Exp/Cntr=0.3,0.1

Type RM Length L Ch R = 1 ,3347.1  ,201.2,199.5,197.7
XS GIS Cut Line= 3
     1593097.248      244835.879     1592842.364      244887.624
     1592681.154      244870.498
#Sta/Elev= 30
       0     870     9.6  866.61    19.3   863.6    28.9  862.24    38.5  862.11
    48.2  861.66    57.8  860.94    67.4  859.72    77.1  857.28     106   846.5
   115.6  843.44   125.2  840.78   134.9  838.44   144.5  837.15   154.1  837.97
   156.7  838.46   163.8  839.79   173.4  841.18   279.2   851.9   288.7  853.16
   298.2  855.07   317.3  859.41   326.8  861.26   345.9  864.64   355.4  866.52
     365  868.89   374.5  871.84   393.6  878.62   412.7  886.01   422.2     890
#Mann= 3 , 0 , 0
       0      .1       0   134.9    .045       0   156.7     .06       0
Bank Sta=134.9,156.7
XS Rating Curve= 0 ,0
Exp/Cntr=0.3,0.1

Type RM Length L Ch R = 1 ,3147.6  ,145.3,146.9,145.1
XS GIS Cut Line= 2
     1593056.181      244630.886     1592690.492      244734.071
#Sta/Elev= 30
       0  879.97     9.7   874.4    19.5  870.08    29.2   866.4      39  863.35
    48.7  861.11    87.7  853.08   116.9  846.89   126.7  844.18   136.4   840.4
   146.1  836.81   148.1  836.49   155.9  835.26   165.6  835.49   175.4  836.42
   185.1  837.44   233.8   841.7   243.6  842.71   253.3   844.5     263  847.46
   272.8  850.74   292.3  857.11     302  860.39   311.8  863.81   321.5  867.43
   331.2  871.23     341  875.17   350.7  879.26   360.5  883.45     380  892.22
#Mann= 3 , 0 , 0
       0      .1       0   148.1    .045       0   165.6     .06       0
Bank Sta=148.1,165.6
XS Rating Curve= 0 ,0
Exp/Cntr=0.3,0.1

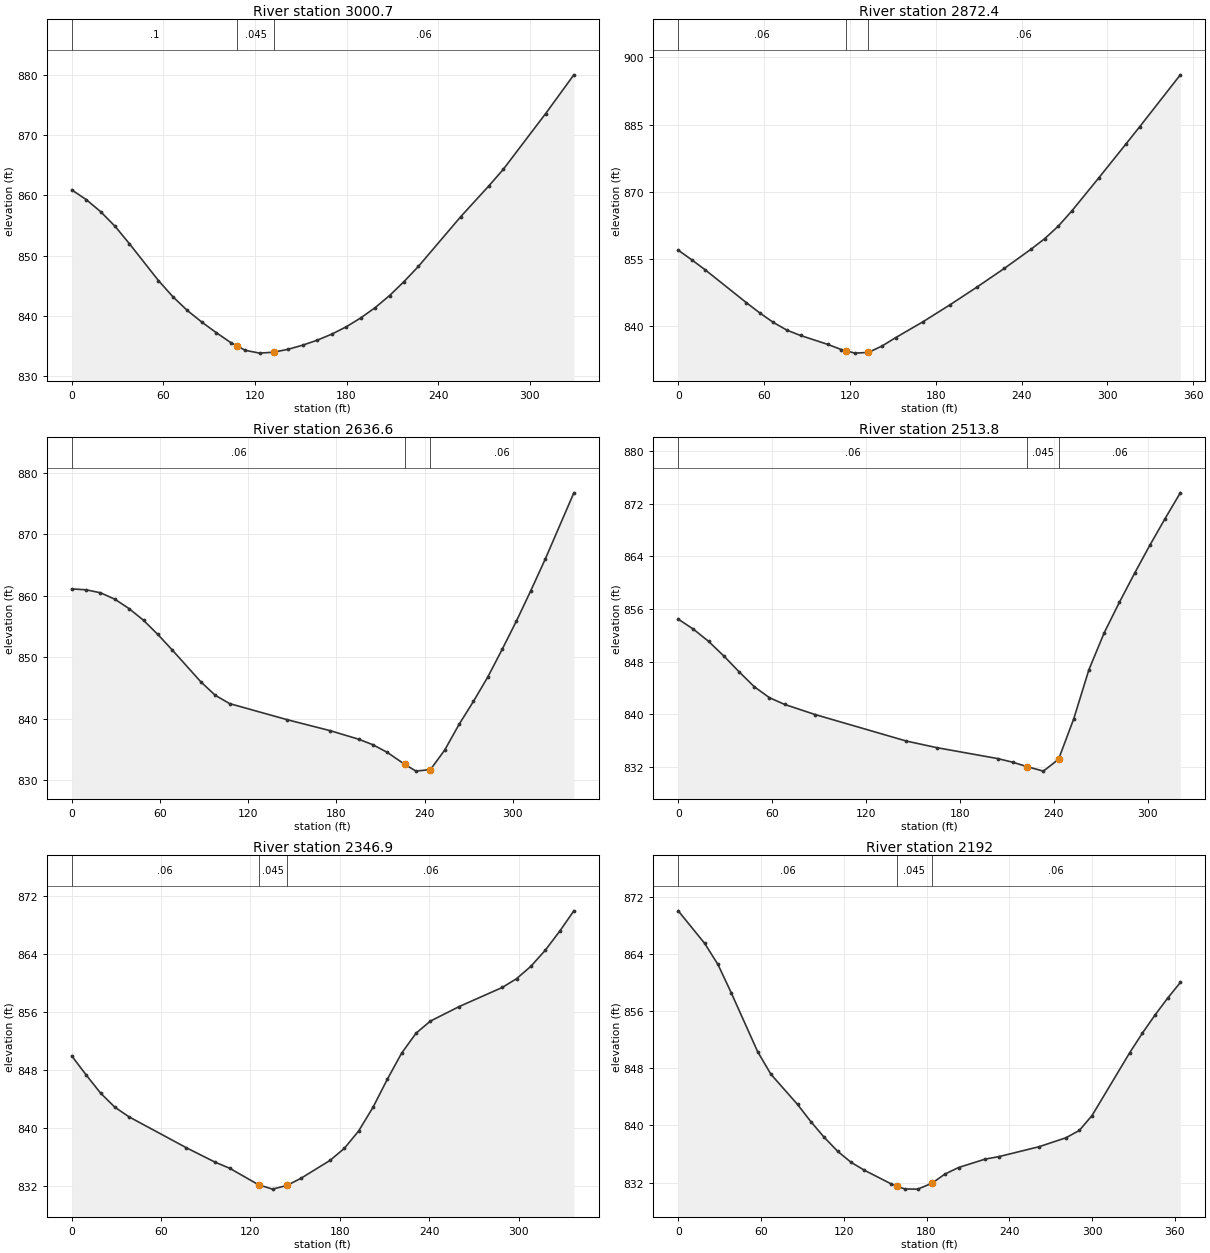
Type RM Length L Ch R = 1 ,3000.7  ,126.8,128.4,129.6
XS GIS Cut Line= 3
      1592961.76      244508.377     1592743.694      244571.772
     1592665.201      244636.572
#Sta/Elev= 30
       0   860.9     9.5  859.29    18.9  857.29    28.4  854.85    37.8  851.96
    56.8  845.85    66.2  843.18    75.7  840.89    85.2  838.96    94.6  837.22
   104.1  835.57   108.3     835   113.6  834.28     123  833.81   132.5  833.97
   141.9  834.46   151.4  835.14   160.9  835.97   170.3  836.96   179.8  838.18
   189.2  839.64   198.7  841.35   208.2  843.37   217.6  845.67   227.1  848.21
   254.8  856.46   273.4  861.62   282.6  864.29   310.4  873.56   328.9     880
#Mann= 3 , 0 , 0
       0      .1       0   108.3    .045       0   132.5     .06       0
Bank Sta=108.3,132.5
XS Rating Curve= 0 ,0
Exp/Cntr=0.3,0.1

Type RM Length L Ch R = 1 ,2872.4  ,228.3,235.7,241.8
XS GIS Cut Line= 3
     1592912.586      244406.048     1592737.406      244449.517
     1592567.761      244432.407
#Sta/Elev= 28
       0  856.87     9.5   854.7      19  852.43    47.5  845.15      57  842.82
    66.5  840.69      76  838.96    85.5  837.77   104.5  835.78     114  834.62
   117.5  834.33   123.5  833.82   132.5  833.97     133  833.98   142.5  835.42
     152  837.29     171  840.82     190  844.64   208.9  848.62   227.9  852.77
   246.8  857.12   256.3  859.47   265.8  862.28   275.2  865.67   294.2  873.13
   313.1  880.68   322.6   884.5     351  896.12
#Mann= 3 , 0 , 0
       0     .06       0   117.5    .045       0   132.5     .06       0
Bank Sta=117.5,132.5
XS Rating Curve= 0 ,0
Exp/Cntr=0.3,0.1

Type RM Length L Ch R = 1 ,2636.6  ,116.5,122.8,128.7
XS GIS Cut Line= 2
     1592966.613      244246.767     1592625.679      244228.867
#Sta/Elev= 28
       0  861.14     9.8  860.99    19.5  860.51    29.3  859.46      39  857.93
    48.8  856.03    58.5  853.73    68.3  851.21    87.8  846.01    97.5  843.84
   107.3  842.48   146.3  839.87   175.6  838.08   195.1  836.68   204.8  835.78
   214.6  834.53   226.5  832.58   234.1  831.49   243.9  831.75   253.6  834.92
   263.4  839.12   273.1  842.83   282.9  846.81   292.6  851.28   302.4  855.93
   312.1  860.84   321.9  865.96   341.4  876.77
#Mann= 3 , 0 , 0
       0     .06       0   226.5    .045       0   243.9     .06       0
Bank Sta=226.5,243.9
XS Rating Curve= 0 ,0
Exp/Cntr=0.3,0.1

Type RM Length L Ch R = 1 ,2513.8  ,165.4,166.9,169.2
XS GIS Cut Line= 2
     1592946.574      244187.636     1592641.339      244089.092
#Sta/Elev= 24
       0  854.46     9.7  852.93    19.4  851.08    29.2  848.84    38.9  846.45
    48.6  844.18    58.3  842.51      68  841.49    87.5  839.95   145.8  835.92
   165.2  834.92   204.1  833.26   213.8   832.7   222.8  832.04   233.3  831.35
     243  833.15   252.7   839.3   262.4  846.77   272.2   852.4   281.9  857.03
   291.6  861.44   301.3  865.68     311  869.72   320.8  873.66
#Mann= 3 , 0 , 0
       0     .06       0   222.8    .045       0     243     .06       0
Bank Sta=222.8,243
XS Rating Curve= 0 ,0
Exp/Cntr=0.3,0.1

Type RM Length L Ch R = 1 ,2346.9  ,154.1,155,153.5
XS GIS Cut Line= 2
     1592959.464      244096.681      1592652.91      243956.439
#Sta/Elev= 27
       0     850     9.6  847.39    19.3  844.88    28.9  842.93    38.5  841.59
      77  837.33    96.3  835.34     106  834.51   125.5  832.22   134.8  831.63
   144.5  832.14   154.1  833.15   173.4  835.59     183  837.25   192.6  839.64
   202.3  842.93   211.9  846.79   221.5  850.39   231.2  853.14   240.8   854.8
   260.1   856.8     289  859.43   298.6  860.64   308.2  862.34   317.8  864.54
   327.5  867.16   337.1     870
#Mann= 3 , 0 , 0
       0     .06       0   125.5    .045       0   144.5     .06       0
Bank Sta=125.5,144.5
XS Rating Curve= 0 ,0
Exp/Cntr=0.3,0.1

Type RM Length L Ch R = 1 ,2192    ,200.2,186,172.3
XS GIS Cut Line= 4
     1593061.258      244045.108     1592990.636       243979.97
     1592812.753      243900.718     1592739.767       243895.66
#Sta/Elev= 30
       0  870.01    19.2  865.45    28.8  862.51    38.4  858.56    57.6  850.31
    67.2  847.16    86.5  842.94    96.1  840.55   105.8  838.35   115.6  836.39
   125.3  834.85     135  833.74   154.5  831.82   158.6  831.52   164.2  831.12
   173.6   831.1   183.7   831.9   193.4  833.21   203.2  834.12   222.6   835.3
   232.4  835.64   261.6  837.03   281.1  838.28   290.8  839.31     300  841.39
   327.4   850.2   336.5  852.91   345.7  855.45   354.8   857.8     364  859.99
#Mann= 3 , 0 , 0
       0     .06       0   158.6    .045       0   183.7     .06       0
Bank Sta=158.6,183.7
XS Rating Curve= 0 ,0
Exp/Cntr=0.3,0.1

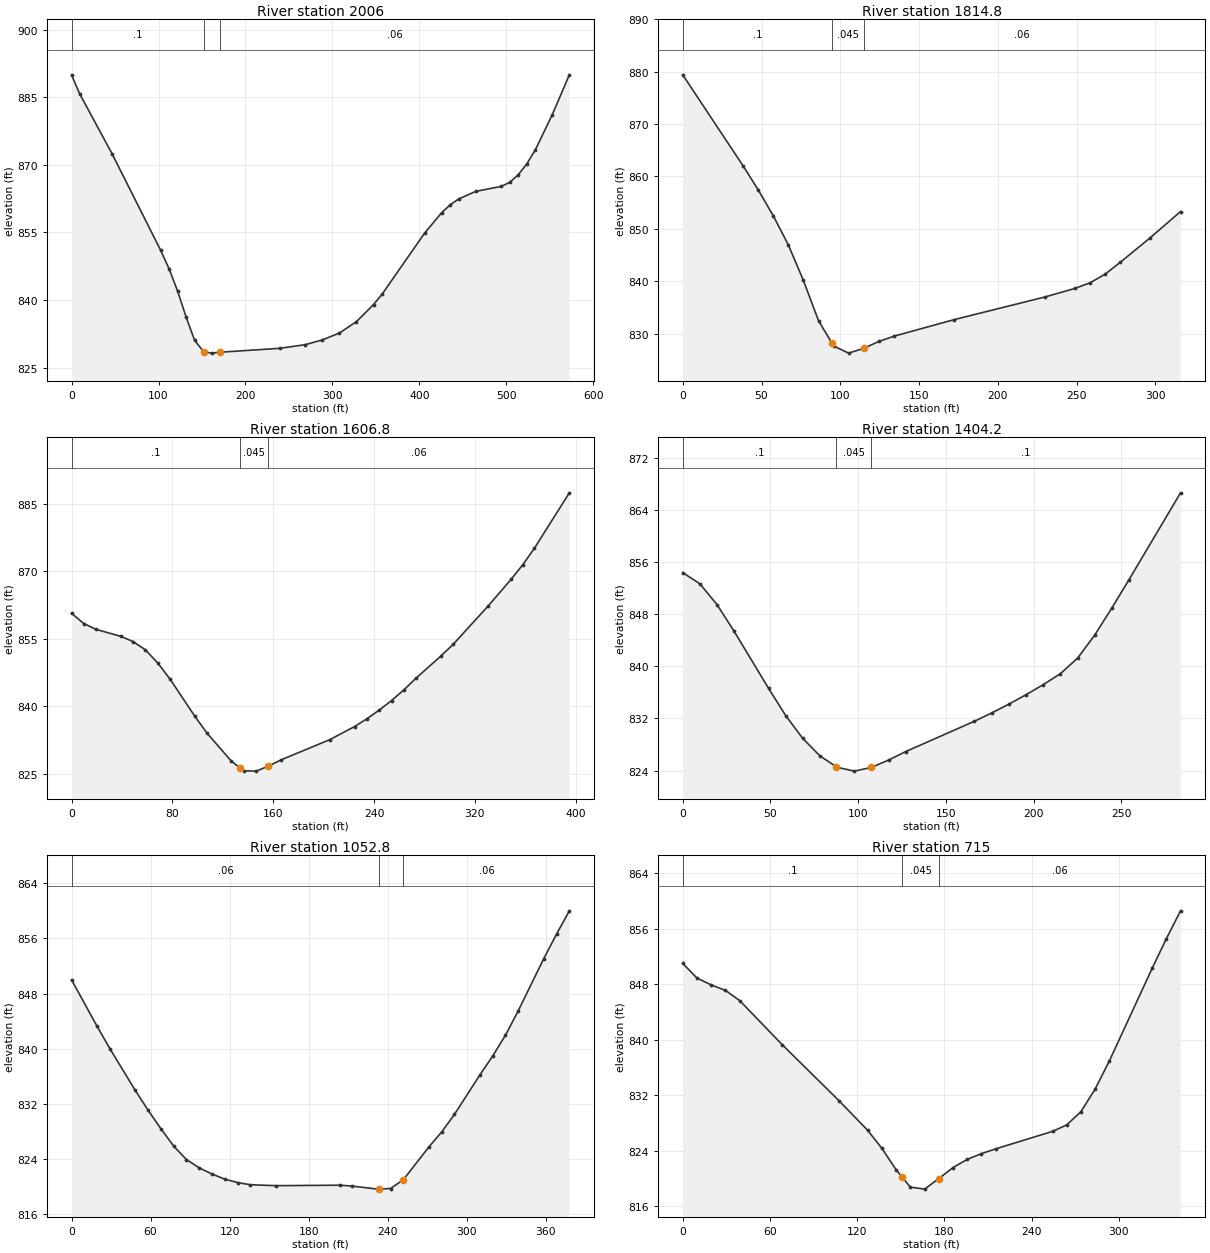
Type RM Length L Ch R = 1 ,2006    ,200.1,191.3,182.6
XS GIS Cut Line= 3
     1593124.443       243726.02     1593034.893      243775.521
     1592572.549      243860.463
#Sta/Elev= 30
       0  889.97     9.3   885.8    46.5   872.5   102.3  851.11   112.1  846.96
   121.9  842.01   131.7  836.25   141.5  831.06   152.1  828.49   161.1  828.22
   170.9  828.42   239.4  829.29   268.8   830.1   288.4  831.16     308  832.67
   327.6  835.21   347.2     839     357  841.27   405.9  854.84   425.5  859.38
   435.3  861.12   445.1  862.44   464.7  864.12     494  865.23   503.8  866.12
   513.6  867.81   523.4  870.21   533.2  873.31   552.8  881.16   572.4     890
#Mann= 3 , 0 , 0
       0      .1       0   152.1    .045       0   170.9     .06       0
Bank Sta=152.1,170.9
XS Rating Curve= 0 ,0
Exp/Cntr=0.3,0.1

Type RM Length L Ch R = 1 ,1814.8  ,210.1,208,205.5
XS GIS Cut Line= 2
     1592953.953      243576.326     1592690.987      243751.611
#Sta/Elev= 21
       0  879.39    38.3  862.03    47.9  857.45    57.5  852.49      67  846.97
    76.6  840.17    86.2  832.49    94.7  828.21    95.8  827.66   105.3   826.3
   114.9  827.21   124.5  828.53   134.1  829.53   172.4   832.7   229.8     837
     249  838.65   258.6  839.72   268.2  841.38   277.7  843.62   296.9  848.34
     316  853.31
#Mann= 3 , 0 , 0
       0      .1       0    94.7    .045       0   114.9     .06       0
Bank Sta=94.7,114.9
XS Rating Curve= 0 ,0
Exp/Cntr=0.3,0.1

Type RM Length L Ch R = 1 ,1606.8  ,201.6,202.6,203.1
XS GIS Cut Line= 3
     1592816.392       243420.13     1592579.169      243608.141
     1592492.097      243638.647
#Sta/Elev= 30
       0  860.68     9.8  858.38    19.5   857.1    39.1  855.56    48.8   854.4
    58.6  852.56    68.4  849.64    78.1  846.08    97.6   837.9   107.4  834.09
   126.9  827.81   133.4  826.41   136.7   825.7   146.5  825.62   156.2  826.73
     166  828.09     205  832.62   224.6  835.53   234.3  837.23   244.1  839.16
   253.9   841.3   263.6  843.64   273.4  846.28   292.9  851.14   302.7  853.75
   330.4  862.25   348.8  868.23     358  871.45   367.3  875.14     395  887.44
#Mann= 3 , 0 , 0
       0      .1       0   133.4    .045       0   156.2     .06       0
Bank Sta=133.4,156.2
XS Rating Curve= 0 ,0
Exp/Cntr=0.3,0.1

Type RM Length L Ch R = 1 ,1404.2  ,334.7,351.3,358.6
XS GIS Cut Line= 3
     1592675.518      243283.333     1592542.061      243382.391
      1592438.52      243437.927
#Sta/Elev= 25
       0  854.43     9.8   852.7    19.6  849.48    29.3   845.4    48.9  836.64
    58.7  832.44    68.4  828.94    78.2  826.25    87.3  824.62      88   824.5
    97.8  823.91   107.5  824.48   117.3  825.61   127.1  826.92   166.2  831.57
     176  832.84   185.8  834.19   195.6  835.65   205.4  837.19   215.2  838.88
     225  841.27   234.7  844.78   244.5  848.96   254.3  853.32   283.7  866.69
#Mann= 3 , 0 , 0
       0      .1       0    87.3    .045       0   107.5      .1       0
Bank Sta=87.3,107.5
XS Rating Curve= 0 ,0
Exp/Cntr=0.3,0.1

Type RM Length L Ch R = 1 ,1052.8  ,339.7,337.8,335.4
XS GIS Cut Line= 2
     1592621.653      243057.564     1592258.411      243161.653
#Sta/Elev= 30
       0     850    19.4  843.26    29.1  840.02    48.4  833.97    58.1   831.1
    67.8  828.43    77.5  825.91    87.2  823.96    96.9  822.76   106.6  821.86
   116.3  821.12     126  820.62   135.6  820.31     155  820.17   203.5  820.24
   213.2  820.11   232.5  819.67   233.7  819.68   242.2  819.76   251.9  821.04
   271.3  825.79     281  827.96   290.7  830.51     310  836.22   319.7  838.96
   329.4  841.97   339.1  845.51   358.5  853.08   368.2  856.63   377.9     860
#Mann= 3 , 0 , 0
       0     .06       0   233.7    .045       0   251.9     .06       0
Bank Sta=233.7,251.9
XS Rating Curve= 0 ,0
Exp/Cntr=0.3,0.1

Type RM Length L Ch R = 1 ,715     ,141.1,139.5,137.8
XS GIS Cut Line= 2
     1592454.917      242752.746     1592129.985      242861.145
#Sta/Elev= 26
       0  850.99     9.8  848.89    19.6   847.9    29.4  847.11    39.2  845.64
    68.5  839.28   107.6  831.21   127.2  826.97     137  824.37   146.8  821.28
     151  820.21   156.6  818.78   166.4  818.49   176.2  820.01     186   821.6
   195.7  822.77   205.5   823.6   215.3  824.29   254.5  826.81   264.2  827.74
     274  829.65   283.8  832.92   293.6  836.98     323   850.3   332.8  854.58
   342.5  858.57
#Mann= 3 , 0 , 0
       0      .1       0     151    .045       0   176.2     .06       0
Bank Sta=151,176.2
XS Rating Curve= 0 ,0
Exp/Cntr=0.3,0.1

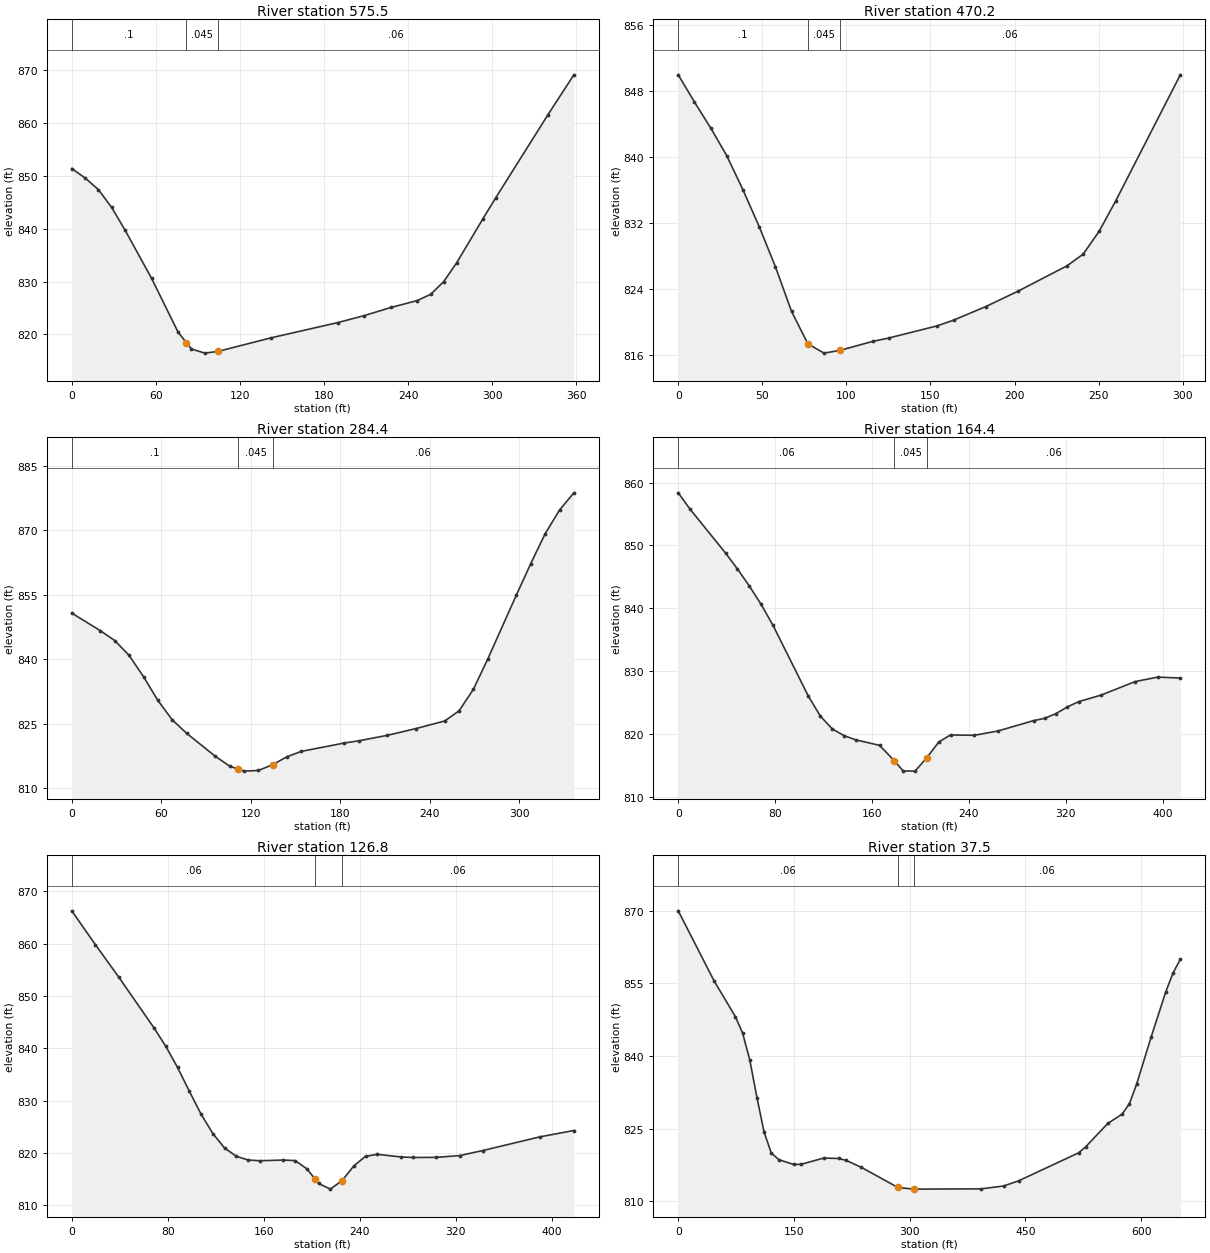
Type RM Length L Ch R = 1 ,575.5   ,105.6,105.3,104.5
XS GIS Cut Line= 3
     1592363.574      242631.577     1592127.175      242730.182
     1592029.323      242759.137
#Sta/Elev= 23
       0  851.37     9.5  849.58      19  847.39    28.5     844      38  839.73
    56.9  830.62    75.9   820.4    81.8  818.44    85.4  817.25    94.9  816.46
   104.4  816.79   142.3  819.36   189.7  822.23   208.7  823.56   227.7  825.09
   246.6  826.41   256.1  827.59   265.4     830   274.7  833.59   293.2  841.81
   302.5  845.85   339.6  861.49   358.2  869.09
#Mann= 3 , 0 , 0
       0      .1       0    81.8    .045       0   104.4     .06       0
Bank Sta=81.8,104.4
XS Rating Curve= 0 ,0
Exp/Cntr=0.3,0.1

Type RM Length L Ch R = 1 ,470.2   ,181.6,185.8,189.6
XS GIS Cut Line= 2
     1592305.467      242541.581     1592032.441      242662.536
#Sta/Elev= 22
       0     850     9.6  846.72    19.3  843.56    28.9  840.18    38.5  836.06
    48.2  831.58    57.8  826.74    67.4  821.32    77.1   817.4    86.7  816.27
    96.3  816.61   115.6  817.69   125.2   818.1   154.1  819.58   163.8  820.27
     183  821.92   202.3   823.8   231.2  826.85   240.8  828.26   250.4  831.06
   260.1  834.69   298.6     850
#Mann= 3 , 0 , 0
       0      .1       0    77.1    .045       0    96.3     .06       0
Bank Sta=77.1,96.3
XS Rating Curve= 0 ,0
Exp/Cntr=0.3,0.1

Type RM Length L Ch R = 1 ,284.4   ,117.8,120,121.5
XS GIS Cut Line= 2
     1592252.273      242385.284     1591925.936      242467.259
#Sta/Elev= 29
       0  850.69    19.2  846.59    28.8   844.3    38.4  840.87    48.1   835.9
    57.7  830.38    67.3  825.88    76.9  822.76    96.1   817.4   105.8   815.1
   111.6  814.39   115.4  813.93     125  814.08   134.6  815.42   144.2  817.27
   153.8  818.52   182.7  820.47   192.3  820.98   211.5  822.26   230.7  823.83
     250   825.6   259.6  827.97   269.2  832.98   278.8     840     298  854.91
   307.6  862.19   317.2  869.11   326.9  874.66   336.5  878.67
#Mann= 3 , 0 , 0
       0      .1       0   111.6    .045       0   134.6     .06       0
Bank Sta=111.6,134.6
XS Rating Curve= 0 ,0
Exp/Cntr=0.3,0.1

Type RM Length L Ch R = 1 ,164.4   ,37.2,37.7,37.9
XS GIS Cut Line= 3
     1592275.779      242274.219     1591986.716      242323.698
     1591865.785       242315.18
#Sta/Elev= 30
       0  858.36     9.8  855.75    39.1  848.78    48.9  846.26    58.6  843.58
    68.4  840.64    78.2  837.31   107.5  826.02   117.3  822.88   127.1  820.85
   136.9  819.77   146.6   819.1   166.2  818.23   178.5  815.76   185.7  814.16
   195.5  814.13   205.3  816.28   215.1  818.76   224.8  819.88   244.4  819.82
   263.9  820.51   293.3  822.15   302.6  822.53   311.9  823.28   321.2  824.33
   330.6  825.17   349.2  826.22   377.2  828.36   395.8  829.07   414.5  828.93
#Mann= 3 , 0 , 0
       0     .06       0   178.5    .045       0   205.3     .06       0
Bank Sta=178.5,205.3
XS Rating Curve= 0 ,0
Exp/Cntr=0.3,0.1

Type RM Length L Ch R = 1 ,126.8   ,91.8,89.3,85.4
XS GIS Cut Line= 3
       1592288.8       242237.76     1591959.599       242288.73
     1591874.249      242284.364
#Sta/Elev= 30
       0  866.24    19.6  859.81    39.2  853.58    68.6  843.88    78.4  840.37
    88.2  836.34      98  831.81   107.8  827.43   117.6  823.73   127.4  820.97
   137.2  819.39     147  818.68   156.8  818.54   176.4  818.67   186.2  818.57
     196     817   202.8  815.06   205.8   814.2   215.6  813.12   225.4  814.75
   235.2  817.56   244.9  819.38   254.7  819.76   274.3  819.27   284.1  819.16
   303.7  819.18   323.3  819.52   342.6  820.48   390.1  823.09   418.6  824.31
#Mann= 3 , 0 , 0
       0     .06       0   202.8    .045       0   225.4     .06       0
Bank Sta=202.8,225.4
XS Rating Curve= 0 ,0
Exp/Cntr=0.3,0.1

Type RM Length L Ch R = 1 ,37.5    ,46.6,37.5,27.9
XS GIS Cut Line= 4
     1592325.018      242191.556     1592217.069      242138.043
     1591835.689      242253.402     1591859.209      242383.017
#Sta/Elev= 30
       0     870    46.3  855.57    74.1  848.12    83.4  844.74    92.7  839.21
     102  831.42   111.2  824.33   120.5     820   130.2   818.6   149.6  817.59
   159.4  817.63   188.5  818.92     208  818.83   217.7  818.43   237.1  817.02
   284.6  812.85   305.1   812.5   392.6  812.56   421.8  813.15   441.2  814.22
   518.9     820   528.3  821.28   556.6  826.06   575.4  828.01   584.8  830.17
   594.2  834.25     613  843.98   631.8  853.23   641.2  857.14   650.7  859.99
#Mann= 3 , 0 , 0
       0     .06       0   284.6    .045       0   305.1     .06       0
Bank Sta=284.6,305.1
XS Rating Curve= 0 ,0
Exp/Cntr=0.3,0.1

Chan Stop Cuts=-1
Use User Specified Reach Order=0
Composite Channel Slope=5